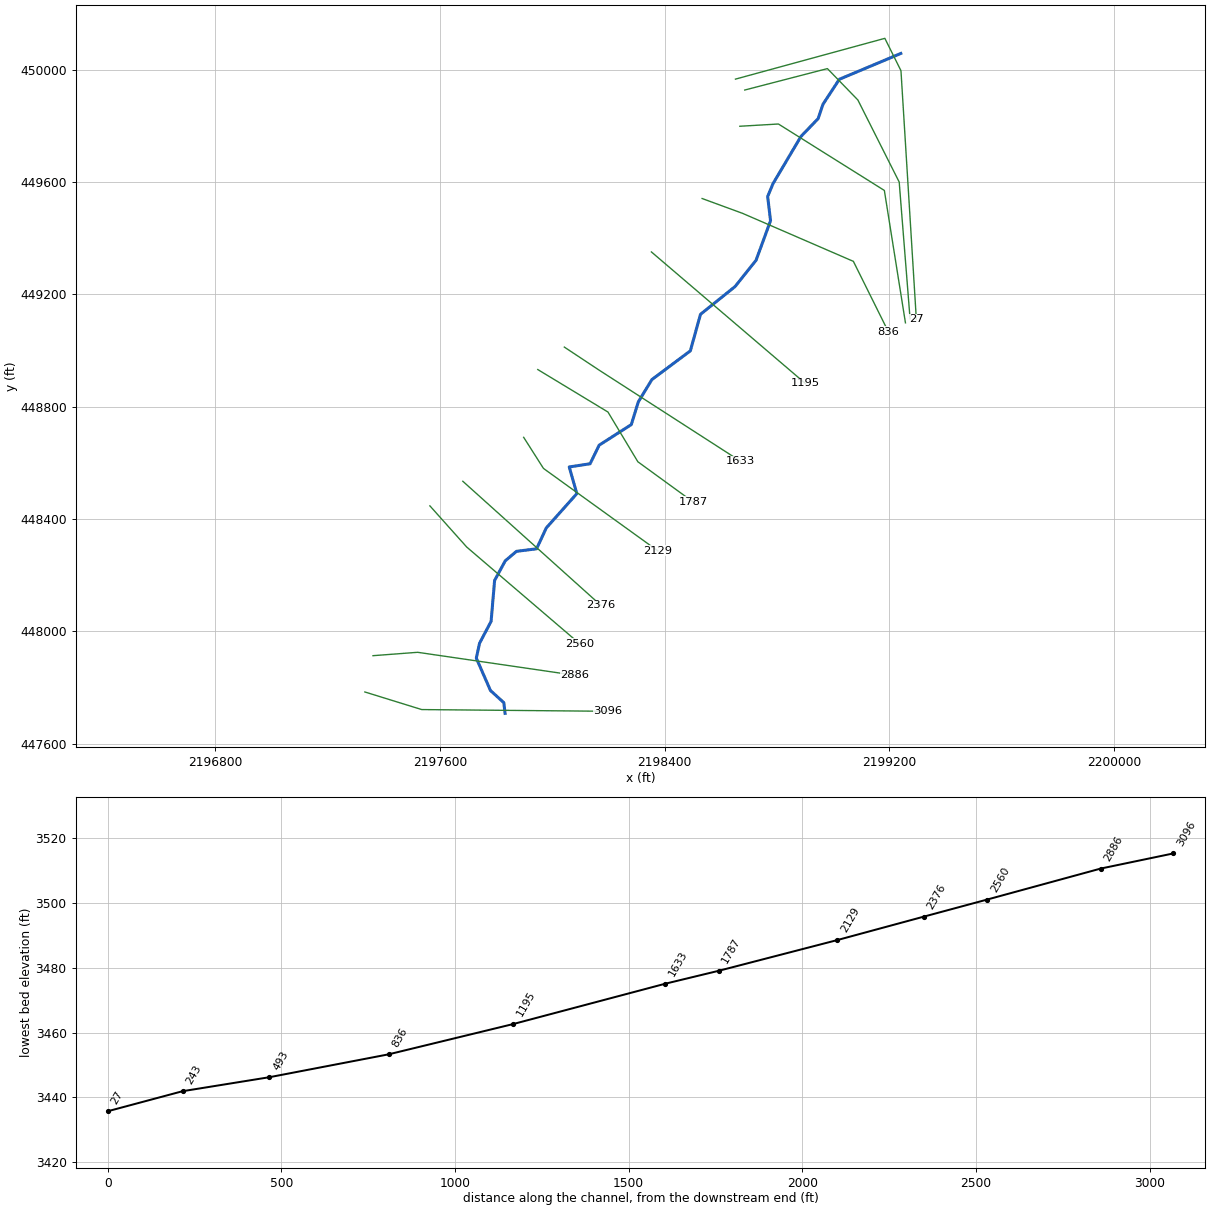
--- MTNLCKRN.prj (project) ---

Proj Title=MTNLCKRN
Current Plan=p01
Default Exp/Contr=0,0
English Units
Geom File=g01
Flow File=f01
Plan File=p01
BEGIN DESCRIPTION:
----------MODEL BY WOOD PLC 2021----------
Stream Name: Mountain Lick Run
Flood Zone: Approximate
Pocahontas County, WV
HEC-RAS Version: RAS 6.1
Vertical Datum: NAVD88
Projection: NAD 1983 StatePlane West Virginia S FIPS 4702 (US Feet)
Terrain: 1-meter LIDAR (FEMA Region III 3DEP collected 2016-2018)
Land Use: 2019 NLCD
Hydrologic Method:
WV SIR2010-5033 regression equations
END DESCRIPTION:
DSS Export Rating Curves= 0
DSS Export Rating Curve Sorted= 0
DSS Export Volume Flow Curves= 0
DXF OffsetX= 0
DXF OffsetY= 0
DXF ScaleX= 0
DXF ScaleY= 0

--- MTNLCKRN.p01 (plan) ---

Plan Title=Floodplain
Program Version=6.00
Short Identifier=Floodplain
Geom File=g01
Flow File=f01
Subcritical Flow
K Sum by GR= 0
Std Step Tol= 0.01
Critical Tol= 0.01
Num of Std Step Trials= 20
Max Error Tol= 0.3
Flow Tol Ratio= 0.001
Split Flow NTrial= 30
Split Flow Tol= 0.02
Split Flow Ratio= 0.02
Log Output Level= 0
Friction Slope Method= 1
Unsteady Friction Slope Method= 2
Unsteady Bridges Friction Slope Method= 1
Parabolic Critical Depth
Global Vel Dist= 0 , 0 , 0
Global Log Level= 0
CheckData=True
Encroach Param=-1 ,0,0, 0
Mapping Interval=1HOUR
Computation Time Step Use Courant=        0
Computation Time Step Use Time Series=    0
Computation Time Step Count To Double=0
Computation Time Step Max Doubling=0
Computation Time Step Max Halving=0
Computation Time Step Residence Courant=0
Run HTab= 0
Run UNet= 0
Run Sediment= 0
Run PostProcess= 0
Run WQNet= 0
Run RASMapper=-1
UNET Theta= 0
UNET Theta Warmup= 0
UNET ZTol= 0
UNET ZSATol= 0
UNET MxIter= 0
UNET Max Iter WO Improvement= 0
UNET MaxInSteps= 0
UNET DtIC= 0
UNET DtMin= 0
UNET MaxCRTS= 0
UNET WFStab= 0
UNET SFStab= 0
UNET WFX= 1
UNET SFX= 1
UNET Gravity=32.174
UNET 1D Methodology=Finite Difference
UNET DSS MLevel= 1
UNET Pardiso=0
UNET DZMax Abort= 0
UNET Use Existing IB Tables= 0
UNET Froude Reduction=False
UNET Froude Limit= 0
UNET Froude Power= 0
UNET D1 Cores= 0
UNET WindReference=Eulerian
UNET WindDragFormulation=Hsu (1988)
UNET D2 Coriolis=0
UNET D2 Cores= 0
UNET D2 Theta= 1
UNET D2 Theta Warmup= 1
UNET D2 Z Tol= 0.01
UNET D2 Volume Tol= 0.01
UNET D2 Max Iterations= 20
UNET D2 Equation= 0
UNET D2 RampUpFraction=0.1
UNET D2 TimeSlices= 1
UNET D2 Turbulence Formulation=Non-Conservative (original)
UNET D2 Eddy Viscosity=0.3
UNET D2 Transverse Eddy Viscosity=0.1
UNET D2 Smagorinsky Mixing=0
UNET D2 BCVolumeCheck=0
UNET D2 Cores=0
UNET D2 SolverType=PARDISO (Direct)
UNET D2 Minimum Iterations= 2147483647
UNET D2 Maximum Iterations= 2147483647
UNET D2 Restart Number= 10
UNET D2 Relaxation Coeff=1.3
UNET D2 SOR Precondition Iterations= 10
UNET D2 ILUT Maximum Fill= 8
UNET D2 ILUT Tolerance=1E-08
UNET D1D2 MaxIter= 0
UNET D1D2 ZTol=0.01
UNET D1D2 QTol=0.1
UNET D1D2 MinQTol=1
Write IC File= 0
Write IC File at Fixed DateTime=0
Write IC File at Sim End=0
Echo Input=False
Echo Parameters=False
Echo Output=False
Write Detailed= 0
HDF Write Warmup=0
HDF Write Time Slices=0
HDF Flush=0
HDF Compression= 1
HDF Chunk Size= 1
HDF Spatial Parts= 1
HDF Use Max Rows=0
HDF Fixed Rows= 1
Calibration Method= 0
Calibration Iterations= 20
Calibration Max Change=0.05
Calibration Tolerance=0.2
Calibration Maximum=1.5
Calibration Minimum=0.5
Calibration Optimization Method= 1
WQ AD Non Conservative
WQ ULTIMATE=-1
WQ Max Comp Step=1HOUR
WQ Output Interval=15MIN
WQ Output Selected Increments= 0
WQ Output face flow=0
WQ Output face velocity=0
WQ Output face area=0
WQ Output face dispersion=0
WQ Output cell volume=0
WQ Output cell surface area=0
WQ Output cell continuity=0
WQ Output cumulative cell continuity=0
WQ Output face conc=0
WQ Output face dconc_dx=0
WQ Output face courant=0
WQ Output face peclet=0
WQ Output face adv mass=0
WQ Output face disp mass=0
WQ Output cell mass=0
WQ Output cell source sink temp=0
WQ Output nsm pathways=0
WQ Output nsm derived pathways=0
WQ Create Restart=0
WQ Fixed Restart=0
WQ System Summary=0
WQ Write To DSS=0
Sorting and Armoring Iterations= 10
XS Update Threshold= 0.02
Bed Roughness Predictor= 0
Hydraulics Update Threshold= 0.02
Energy Slope Method= 1
Volume Change Method= 1
Sediment Retention Method= 0
Sediment TS Multiplier= 1
Warm Up Method= 0
XS Weighting Method= 0
Number of US Weighted Cross Sections= 1
Number of DS Weighted Cross Sections= 1
Upstream XS Weight=0
Main XS Weight=1
Downstream XS Weight=0
Number of DS XS's Weighted with US Boundary= 1
Upstream Boundary Weight= 1
Weight of XSs Associated with US Boundary= 0
Number of US XS's Weighted with DS Boundary= 1
Downstream Boundary Weight= 0.5
Weight of XSs Associated with DS Boundary= 0.5
Percentile Method= 0
Sediment Output Level= 3
Mass or Volume Output= 0
Output Increment Type= 1
Profile and TS Output Increment= 1
Transport Output Increment 1
XS Output Flag= 0
XS Output Increment= 10
Read HDF5 Sediment Hotstart= 0
Sediment Hotstart Type= 0
Write Gradation File= 0
Read Gradation Hotstart= 0
Write HDF5 File= 1
Write Binary Output= 1
Write DSS Sediment File= 0
DSS Sediment Output Type= 1
SV Curve= 0
Specific Gage Flag= 0
Subcell Erosion Methods= 0
Subcell Deposition Methods= 0
Advection Scheme= 1
Matrix Solver= 0
Implicit Weighting Factor= 1
Maximum Outer Loop Convergence Iterations= 5
Convergence Maximum Absolute= 0.001
Convergence RMSE= 0.0001
Grain Fractions Max Abs Error= 0.001
Max Subgrid Regions= 1
Max Subgrid Length Scale= 3.402823E+38
Initial Layer Thickness= 3.402823E+38
Min Layer Thickness= 3.402823E+38
Max Layer Thickness= 3.402823E+38
Number of Layers= 5

--- MTNLCKRN.f01 (steady flow) ---

Flow Title=Flow
Program Version=6.10
Number of Profiles= 6
Profile Names=01pct,10pct,04pct,02pct,0_2pct,01plus
River Rch & RM=MTNLCKRN,Main            ,3096
     575     304     404     487     803     850
Boundary for River Rch & Prof#=MTNLCKRN,Main            , 1
Up Type= 0
Dn Type= 3
Dn Slope=0.02273
Boundary for River Rch & Prof#=MTNLCKRN,Main            , 2
Up Type= 0
Dn Type= 3
Dn Slope=0.02273
Boundary for River Rch & Prof#=MTNLCKRN,Main            , 3
Up Type= 0
Dn Type= 3
Dn Slope=0.02273
Boundary for River Rch & Prof#=MTNLCKRN,Main            , 4
Up Type= 0
Dn Type= 3
Dn Slope=0.02273
Boundary for River Rch & Prof#=MTNLCKRN,Main            , 5
Up Type= 0
Dn Type= 3
Dn Slope=0.02273
Boundary for River Rch & Prof#=MTNLCKRN,Main            , 6
Up Type= 0
Dn Type= 3
Dn Slope=0.02273
DSS Import GetInterval= 0
DSS Import GetPeak= 0
DSS Import FillOption= 0

--- MTNLCKRN.g01 (geometry) ---

Geom Title=Geometry
Program Version=6.10

River Reach=MTNLCKRN        ,Main
Reach XY= 30
2197831.74499531447707.5790565612197827.25812764447745.808966979
2197779.83400989447788.9260067342197729.37160207447904.290056477
2197740.86623648  447957.3485192 2197782.0273176448035.312146417
2197794.50819314448180.9550783042197832.39788114448250.784663066
2197872.30134463 448284.620225312197943.97935089 448293.60314697
2197978.51012172448367.9143500632198087.33372296448490.089958727
2198060.29068665448585.0721348832198134.51471197 448596.47771797
 2198166.9333013448662.7569362222198281.28116973448735.866698146
2198306.23027229448816.8471766182198354.59893647448896.278122723
2198491.58553913448998.6046897322198527.62943031449128.602789313
2198650.88672972 449227.595701562198725.56801081449321.183112815
2198777.12007305 449461.800941812198766.85697022 449548.18593964
2198785.90089539449593.9240371442198885.41414781449761.980131477
2198946.58594146 449825.503954562198963.91891205449876.744009554
2199022.08086923 449965.607020812199241.11586422450057.632755399

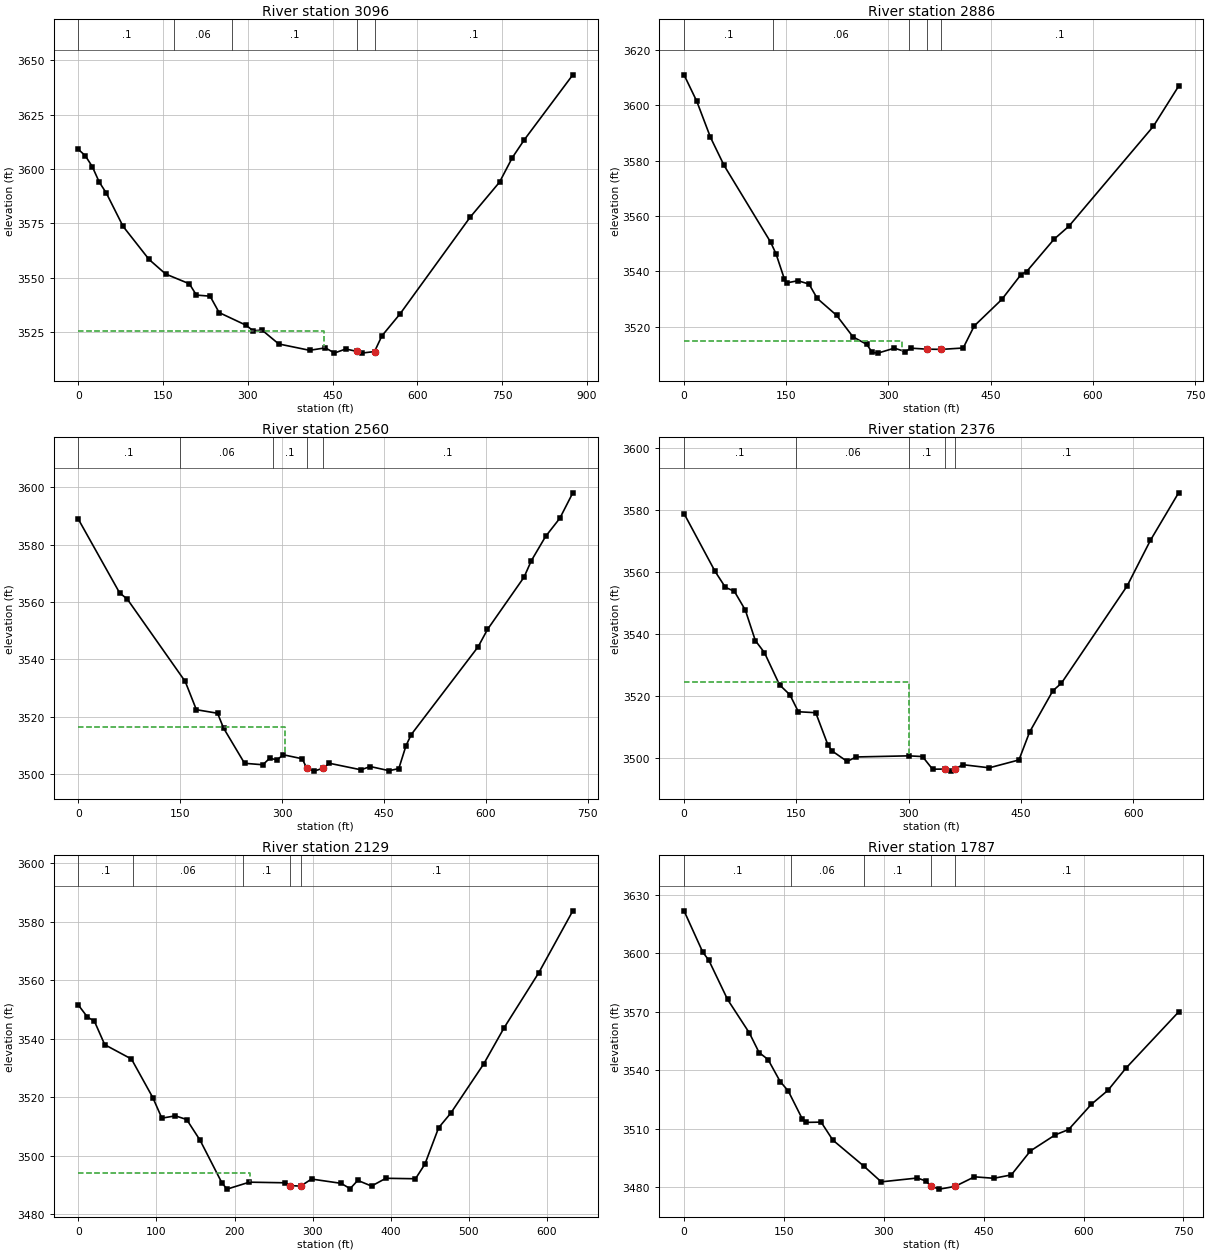
Type RM Length L Ch R = 1 ,3096    ,209.6,209.6,209.6
XS GIS Cut Line= 3
2197332.47099397447783.7944205972197534.99281204447721.128954347
2198197.83309568447714.995977173
#Sta/Elev= 30
       0 3609.03    12.3 3606.13    24.8 3601.07      37 3594.01    49.8 3588.81
    79.2  3573.6   125.3 3558.33   154.6 3551.64   196.5 3547.15     209 3541.95
   233.2 3541.45   249.2  3533.9   297.2 3528.03   309.2 3525.52   325.2 3525.83
   354.6 3519.46   409.2 3516.54   437.2 3517.66   453.2 3515.29   473.2 3517.14
   493.2 3516.03   501.2 3515.24  524.13 3515.97   537.2  3523.2   569.2 3533.27
   693.2 3577.77   745.2  3593.9     768 3605.26   789.2 3613.47   874.9 3643.31
#Mann= 5 ,-1,0
       0      .1       0     170     .06       0     272      .1       0
   493.2    .045       0  524.13      .1       0
#XS Ineff= 2 , 0
          434.25 3525.43
Permanent Ineff=
       F       F
Bank Sta=493.2,524.13
XS Rating Curve= 0 ,0
Exp/Cntr=0.3,0.1

Type RM Length L Ch R = 1 ,2886    ,333.3,326.4,315.2
XS GIS Cut Line= 3
2197361.51596103447913.0306003552197520.52457108447925.048592101
2198080.96021744447843.222407814
#Sta/Elev= 30
       0 3610.89    18.7 3601.35    38.8 3588.35    58.8 3578.21     127 3550.61
     135 3546.36   147.1  3537.4   151.1  3535.9   167.2 3536.66   183.4 3535.46
   195.5 3530.27   223.8 3524.21     248 3516.42   268.1 3513.72   276.3  3510.8
   284.4 3510.56   308.7 3512.35   324.8  3511.1   332.9 3512.35   356.6 3511.99
   377.7 3511.91   409.7 3512.41   425.9 3520.36   466.3  3529.9   494.6  3538.9
   502.7 3539.94   543.1 3551.64   564.7 3556.29   688.7 3592.31   725.8 3606.78
#Mann= 5 ,-1,0
       0      .1       0     130     .06       0  329.46      .1       0
   356.6    .045       0   377.7      .1       0
#XS Ineff= 2 , 0
             320    3515
Permanent Ineff=
       F       F
Bank Sta=356.6,377.7
XS Rating Curve= 0 ,0
Exp/Cntr(USF)=0,0
Exp/Cntr=0.3,0.1

Type RM Length L Ch R = 1 ,2560    ,182.9,183.5,179.2
XS GIS Cut Line= 3
     2197564.097      448446.5362197695.04773919448300.003968435
2198098.63836742447954.525841871
#Sta/Elev= 30
       0 3588.87    60.8 3563.17    72.2 3560.95   157.4 3532.26   173.8 3522.43
     205 3521.19   213.8 3516.03   244.7 3503.75   271.7 3503.24   281.6  3505.5
   292.8 3504.96   301.5 3506.73   329.6 3505.33   336.2 3502.05   346.8 3501.02
  360.26 3502.02   369.5 3503.76   416.1 3501.48   429.7 3502.62   457.5 3501.17
   471.7 3501.91   482.3 3509.87     490 3513.76   588.4 3544.34   602.2 3550.39
   656.1 3568.66   666.6  3574.3   687.7 3582.81   708.7 3589.16   727.8 3598.02
#Mann= 5 ,-1,0
       0      .1       0     150     .06       0  286.52      .1       0
   336.2    .045       0  360.26      .1       0
#XS Ineff= 2 , 0
          304.08 3516.34
Permanent Ineff=
       F       F
Bank Sta=336.2,360.26
XS Rating Curve= 0 ,0
Exp/Cntr=0.3,0.1

Type RM Length L Ch R = 1 ,2376    ,246.6,247.9,248.7
XS GIS Cut Line= 2
2197681.35367301448534.067663994   2198172.59402448092.543207544
#Sta/Elev= 30
       0 3578.83    41.4 3560.19    55.2 3555.03    67.2 3553.75    81.9 3547.66
    95.2 3537.86   107.4 3533.95   127.5 3523.58   141.4 3520.35   152.7 3514.88
   175.9 3514.57     192 3504.28   197.4 3502.28   217.9 3498.84   229.7 3500.29
     300 3500.65   318.5 3500.42   331.9 3496.35   348.4 3496.38   356.7 3495.72
   362.3 3496.41   372.3  3497.8   407.7 3496.79   447.3 3499.33   461.5 3508.32
   492.6 3521.65     504 3524.09   591.8 3555.48   622.9  3570.2   660.5 3585.52
#Mann= 5 ,-1,0
       0      .1       0     150     .06       0     300      .1       0
   348.4    .045       0   362.3      .1       0
#XS Ineff= 2 , 0
          300.89 3524.59
Permanent Ineff=
       F       F
Bank Sta=348.4,362.3
XS Rating Curve= 0 ,0
Exp/Cntr(USF)=0,0
Exp/Cntr=0.3,0.1

Type RM Length L Ch R = 1 ,2129    ,314.4,342,290.2
XS GIS Cut Line= 3
2197897.95930148448690.6711981512197968.44783549448579.903501844
2198375.55508295448286.441033708
#Sta/Elev= 30
       0 3551.55    11.6 3547.45    20.7 3545.95    33.9 3537.95    68.1 3533.04
    95.4 3519.86     107 3512.82   124.4  3513.6   138.8 3512.34     156 3505.22
   183.8 3490.71   190.4 3488.53     219 3490.91   264.1  3490.7   270.6  3489.7
   284.9 3489.59   298.6 3491.98   336.5 3490.51     348 3488.69   357.8 3491.52
   375.4 3489.58   393.8 3492.24   431.7 3492.08   443.8 3497.11   461.3 3509.53
   476.9 3514.54     519 3531.35   545.2 3543.76   589.5 3562.56   633.1 3583.75
#Mann= 5 ,-1,0
       0      .1       0      70     .06       0  211.29      .1       0
   270.6    .045       0   284.9      .1       0
#XS Ineff= 2 , 0
             220    3494
Permanent Ineff=
       F       F
Bank Sta=270.6,284.9
XS Rating Curve= 0 ,0
Exp/Cntr(USF)=0,0
Exp/Cntr=0.3,0.1

Type RM Length L Ch R = 1 ,1787    ,149.2,153.3,171.3
XS GIS Cut Line= 4
2197948.22820549 448931.966081772198198.14999327448780.668138496
2198304.61891631 448603.593508592198501.86660532448460.140643856
#Sta/Elev= 30
       0 3621.67      28 3600.59    37.3 3596.28    65.4 3576.23    98.1 3559.08
   112.7 3549.05   126.2 3545.45   144.4 3534.16   156.4 3529.41   177.6 3515.01
   182.6 3513.24   205.9 3513.38   223.4 3504.19     270 3490.83   296.2 3482.77
   350.4 3484.74   363.2 3483.21   370.9 3480.45   383.6 3479.04   406.9 3480.43
   436.2 3485.35   465.2  3484.6   491.5 3486.33   520.2 3498.62   557.4 3506.84
   577.5 3509.57   611.7 3522.51   636.7 3529.71   663.4 3540.95   742.7 3569.83
#Mann= 5 ,-1,0
       0      .1       0     160     .06       0     270      .1       0
   370.9    .045       0   406.9      .1       0
Bank Sta=370.9,406.9
XS Rating Curve= 0 ,0
Exp/Cntr(USF)=0,0
Exp/Cntr=0.3,0.1

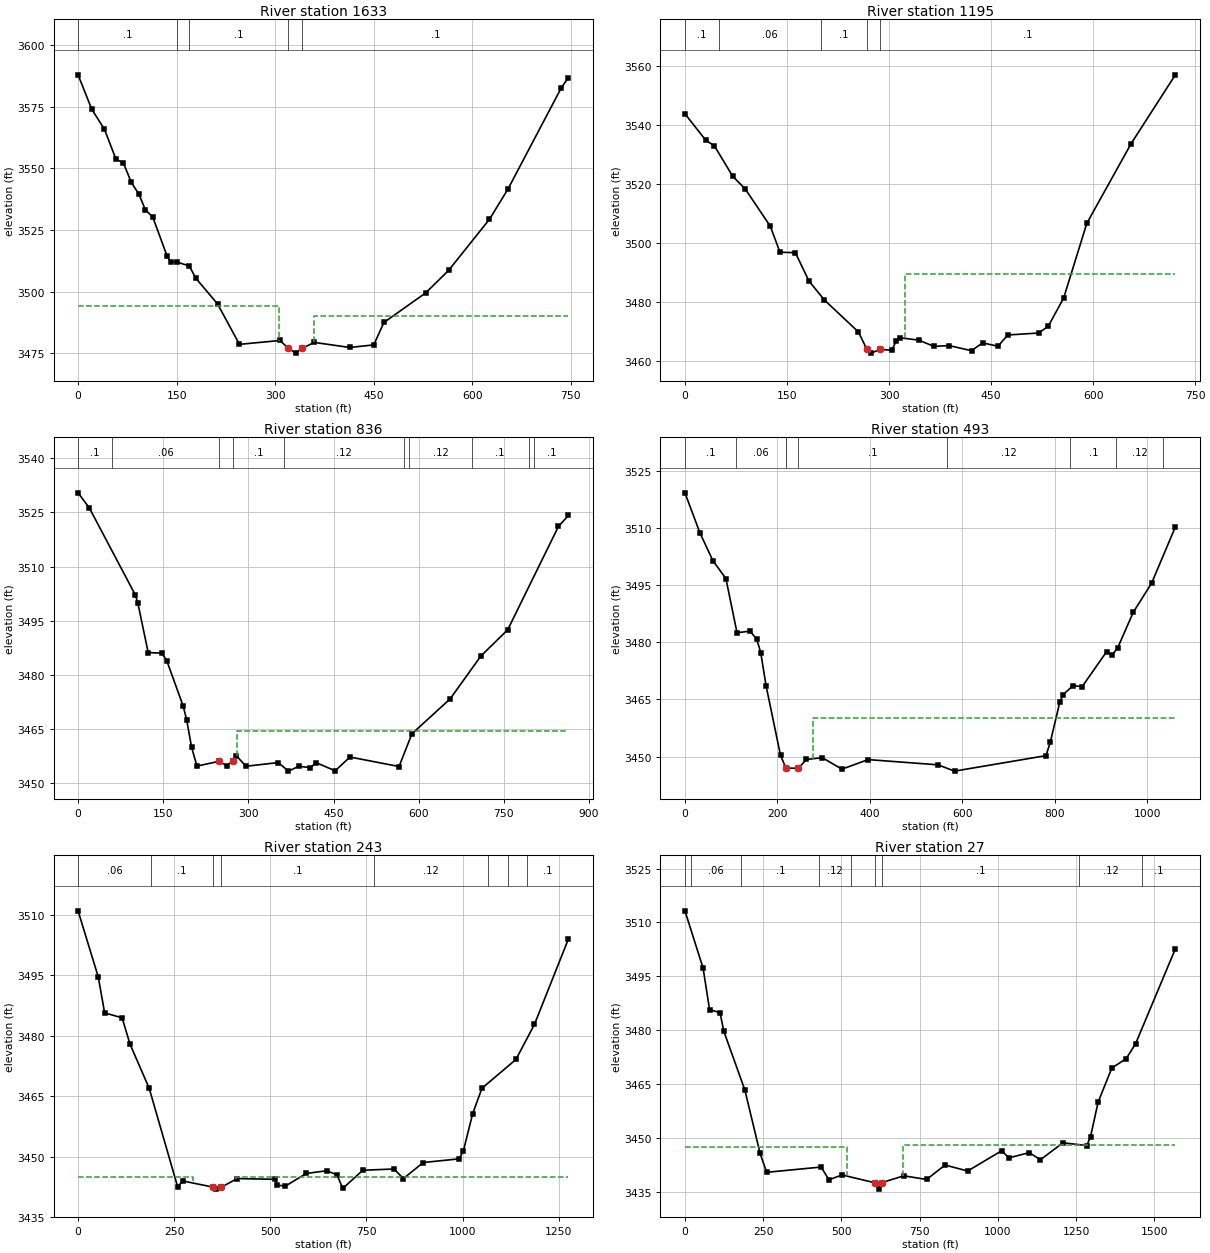
Type RM Length L Ch R = 1 ,1633    ,439.1,438.4,435.4
XS GIS Cut Line= 3
 2198042.7724802449011.9454688232198165.84769832448930.428116563
2198669.33722698448605.957086978
#Sta/Elev= 30
       0 3587.84    20.9 3573.85    40.1 3565.83    57.8 3553.57    68.9 3552.25
    80.9 3544.29    92.5 3539.55   102.4 3533.19   113.7  3530.2   135.4 3514.49
   140.8 3511.92   149.9 3512.04   169.4 3510.39   178.9 3505.55   212.3 3495.02
   245.7 3478.63   307.4 3480.19   319.8 3477.13   331.2 3475.07   341.2 3477.05
   359.8 3479.41   413.5 3477.36   450.2 3478.41   465.6 3487.49   529.3 3499.49
     564 3508.57   626.3 3529.31   654.8 3541.71   735.7  3582.6   746.6 3586.74
#Mann= 5 ,-1,0
       0      .1       0   149.9     .06       0   169.4      .1       0
   319.8    .045       0   341.2      .1       0
#XS Ineff= 2 , 0
          305.18 3494.17   359.8            3490
Permanent Ineff=
       F       F
Bank Sta=319.8,341.2
XS Rating Curve= 0 ,0
Exp/Cntr(USF)=0,0
Exp/Cntr=0.3,0.1

Type RM Length L Ch R = 1 ,1195    ,353.5,358.7,363.8
XS GIS Cut Line= 2
2198352.85809468449350.8019135122198901.10224811 448882.47673288
#Sta/Elev= 30
       0 3543.89    30.7 3534.88    43.2 3533.02    70.2 3522.69    88.7 3518.33
   125.4 3505.76   139.7 3496.89   162.4 3496.72   182.2 3487.15   204.9 3480.69
     255 3469.82   267.4 3463.95   273.5 3462.62   287.2 3463.89   304.3 3463.57
   310.4 3466.76   316.6 3467.82     344 3467.02   365.8 3464.92   388.4 3465.17
   421.3 3463.45   437.6  3466.1   460.3 3464.96   474.5 3468.78   519.9 3469.45
   534.1 3471.73   556.8 3481.35   590.8 3506.69     656 3533.78     721 3557.12
#Mann= 5 ,-1,0
       0      .1       0      50     .06       0     200      .1       0
   267.4    .045       0   287.2      .1       0
#XS Ineff= 2 , 0
                          323.66         3489.65
Permanent Ineff=
       F       F
Bank Sta=267.4,287.2
XS Rating Curve= 0 ,0
Exp/Cntr(USF)=0,0
Exp/Cntr=0.3,0.1

Type RM Length L Ch R = 1 ,836     ,345.1,343.1,339.1
XS GIS Cut Line= 4
2198533.47497321449541.0090687862198677.32912426449488.262546735
2199072.12884991449317.2359449342199196.80244749 449066.29037033
#Sta/Elev= 30
       0 3530.45    19.9 3526.25   100.9 3502.11   105.1 3500.03   123.5 3486.15
   147.7 3485.99   156.3 3483.88   185.1 3471.33   191.2 3467.55   199.9 3459.92
   209.4 3454.68   247.9 3455.98   261.6 3454.84  272.66 3456.02   278.4  3457.6
   295.8 3454.63   352.5 3455.65   370.6 3453.28   388.9 3454.63   409.2 3454.24
   419.3 3455.64   452.7 3453.37   478.9 3457.19   565.3 3454.56     588 3463.64
   655.2  3473.3   709.4 3485.19   756.6 3492.47   846.1 3521.15   863.7 3524.19
#Mann= 10 ,-1,0
       0      .1       0      60     .06       0   247.9    .045       0
  272.66      .1       0  363.22     .12       0  573.22      .1       0
  583.22     .12       0  693.47      .1       0  793.47     .12       0
  803.47      .1       0
#XS Ineff= 2 , 0
                          279.45         3464.41
Permanent Ineff=
       F       F
Bank Sta=247.9,272.66
XS Rating Curve= 0 ,0
Exp/Cntr(USF)=0,0
Exp/Cntr=0.3,0.1

Type RM Length L Ch R = 1 ,493     ,253.6,250.2,245.8
XS GIS Cut Line= 4
2198667.73884752449798.3481612152198805.19948075449806.340058495
2199182.41703238449569.7798989952199257.54086682449098.257959451
#Sta/Elev= 30
       0 3519.15    32.5 3508.62    60.5 3501.36    88.6 3496.68   112.6 3482.49
   140.7 3482.91   155.4 3480.77   163.9 3477.27   175.5 3468.55   206.7 3450.33
  218.45 3447.01   245.3 3446.99   262.6 3449.28     297 3449.75   339.5 3446.75
   396.2 3449.25   547.3 3447.88   582.9 3446.23   780.7 3450.29   790.1 3453.87
   810.4 3464.27   817.6 3466.26   838.7 3468.58     859  3468.4   911.6  3477.5
   923.9  3476.7   935.9  3478.6   969.3 3487.84  1008.9 3495.45  1060.4 3510.21
#Mann= 9 ,-1,0
       0      .1       0     110     .06       0  217.69      .1       0
  218.45    .045       0   245.3      .1       0  567.69     .12       0
  832.95      .1       0  932.95     .12       0 1032.95      .1       0
#XS Ineff= 2 , 0
                          277.86         3460.04
Permanent Ineff=
       F       F
Bank Sta=218.45,245.3
XS Rating Curve= 0 ,0
Exp/Cntr(USF)=0,0
Exp/Cntr=0.3,0.1

Type RM Length L Ch R = 1 ,243     ,221.8,215.5,208
XS GIS Cut Line= 5
2198685.30976279449927.3060915712198979.63982179450003.654866274
2199088.07721195449891.8979641732199235.24224145449599.780913135
2199273.96988079449112.919161406
#Sta/Elev= 30
       0 3511.03    52.5 3494.62    69.1 3485.68   114.5 3484.47   135.1 3477.91
   184.8    3467   259.2  3442.4   271.6 3443.95     3503442.431   357.7 3441.91
  372.77  3442.4   413.7 3444.53   512.1 3444.35   518.5  3442.9     539 3442.66
   593.4  3445.8   646.7 3446.47   673.4 3445.47   688.2 3442.07   740.5  3446.6
   821.6 3446.91   845.9 3444.54   897.7 3448.52   990.9 3449.43    1002 3451.43
  1026.2 3460.67  1050.3 3466.97  1138.6 3474.11  1186.7 3482.81  1275.3 3504.08
#Mann= 8 ,-1,0
       0     .06       0     190      .1       0     350    .045       0
  372.77      .1       0  769.79     .12       0 1066.88      .1       0
 1116.88     .12       0 1166.88      .1       0
#XS Ineff= 2 , 0
             300    3445     410            3445
Permanent Ineff=
       F       F
Bank Sta=350,372.77
XS Rating Curve= 0 ,0
Exp/Cntr(USF)=0,0
Exp/Cntr=0.3,0.1

Type RM Length L Ch R = 1 ,27      ,27,27,27
XS GIS Cut Line= 4
2198652.16256291449966.1498615812199184.18411448450111.422830273
2199241.55472705 449996.190125842199296.33617816449110.586586375
#Sta/Elev= 30
       0 3513.24    58.1 3497.25    78.8 3485.69     112  3484.9   124.4 3479.66
   191.4 3463.36   240.2 3445.69   261.2 3440.42   435.4 3441.88   460.3 3438.31
   501.7 3439.69   606.9  3437.5     621 3435.73  629.01 3437.53   699.3 3439.44
   772.3 3438.42   831.5 3442.44   903.7 3440.77  1011.9  3446.4  1035.9 3444.44
  1100.7  3445.9  1136.1 3443.91  1208.2 3448.64  1284.4 3447.86  1296.4 3450.34
  1320.5 3459.95  1364.5 3469.47  1410.2 3472.05  1440.4 3476.24  1567.5 3502.65
#Mann= 9 ,-1,0
       0      .1       0      20     .06       0     180      .1       0
     430     .12       0     530      .1       0   606.9    .045       0
  629.01      .1       0 1260.22     .12       0 1460.22      .1       0
#XS Ineff= 2 , 0
          517.15  3447.4  698.32         3448.12
Permanent Ineff=
       F       F
Bank Sta=606.9,629.01
XS Rating Curve= 0 ,0
Exp/Cntr(USF)=0,0
Exp/Cntr=0.3,0.1
LCMann Table=0

Chan Stop Cuts=-1
Use User Specified Reach Order=0
Composite Channel Slope=5